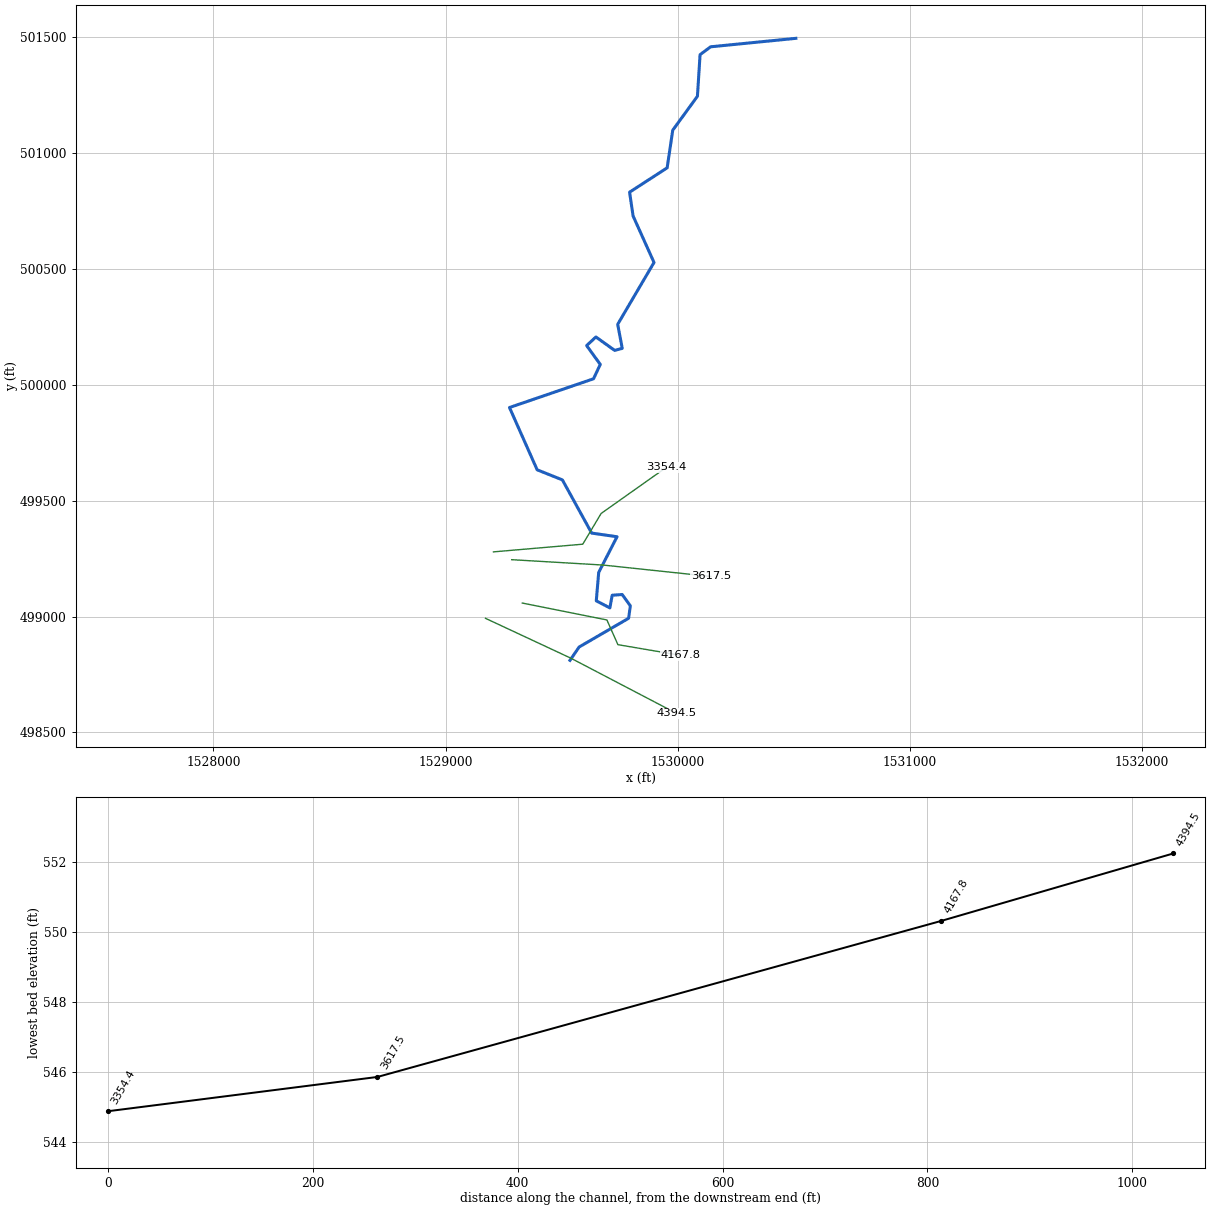
--- WALKERBR.prj (project) ---

Proj Title=WALKERBR
Current Plan=p01
Default Exp/Contr=0,0
English Units
Geom File=g01
Flow File=f01
Plan File=p01
BEGIN DESCRIPTION:
END DESCRIPTION:
DSS Export Rating Curves= 0
DSS Export Rating Curve Sorted= 0
DSS Export Volume Flow Curves= 0
DXF OffsetX= 0
DXF OffsetY= 0
DXF ScaleX= 0
DXF ScaleY= 0

--- WALKERBR.p01 (plan) ---

Plan Title=Floodplain
Program Version=4.00
Geom File=g01
Flow File=f01
K Sum by GR=0
Std Step Tol=0.01
Critical Tol=0.01
Num of Std Step Trials=20
Max Error Tol=0.3
Flow Tol Ratio=0.001
Split Flow NTrial=30
Split Flow Tol=0.02
Split Flow Ratio=0.02
Log Output Level=0
Friction Slope Method=1
Unsteady Friction Slope Method=2
Unsteady Bridges Friction Slope Method=1
Global Log Level=0
CheckData=False
Run HTab=0
Run UNet=0
Run PostProcess=0
UNET Theta=0
UNET Theta Warmup=0
UNET ZTol=0
UNET ZSATol=0
UNET MxIter=0
UNET MaxInSteps=0
UNET DtIC=0
UNET DtMin=0
UNET MaxCRTS=0
UNET WFStab=0
UNET SFStab=0
UNET WFX=0
UNET SFX=0
UNET DSS MLevel=0
UNET DZMax Abort=0
UNET Convert EG Bridges=0
UNET Use Existing IB Tables=0
UNET Froude Limit=0
UNET Froude Power=0
Write IC File=0
Echo Input=False
Echo Output=False
Write Detailed=0

--- WALKERBR.f01 (steady flow) ---

Flow Title=NFF Regression Equation
Program Version=4.00
Number of Profiles=1
Profile Names=P100yr
River Rch & RM=WALKERBR,Main      ,4394.5
     402
Boundary for River Rch & Prof#=WALKERBR,Main      ,1
Up Type=0
Dn Type=3
Dn Slope=0.006773

--- WALKERBR.g01 (geometry) ---

Geom Title=USGS 10m DEM
Program Version=4.00

River Reach=WALKERBR        ,Main
Reach XY= 30
     1529536.146      498811.371      1529575.36      498868.726
       1529788.5      498992.872      1529796.21      499046.412
     1529760.917      499095.473     1529717.887      499092.276
     1529707.949      499037.735     1529649.371      499068.253
     1529659.859      499190.983     1529738.738      499344.761
     1529629.491      499360.608     1529503.487      499590.119
       1529394.7       499633.74     1529275.647      499902.579
     1529637.558      500026.586     1529666.607      500088.565
      1529607.86      500169.762     1529647.702       500207.08
     1529728.561      500149.086     1529761.201      500157.827
     1529741.572       500261.64     1529898.074      500528.553
      1529807.94      500729.264      1529792.86      500832.025
     1529954.569      500936.995     1529978.788      501099.613
     1530085.033      501245.979     1530096.408      501425.538
     1530142.008      501459.526     1530508.961      501496.012

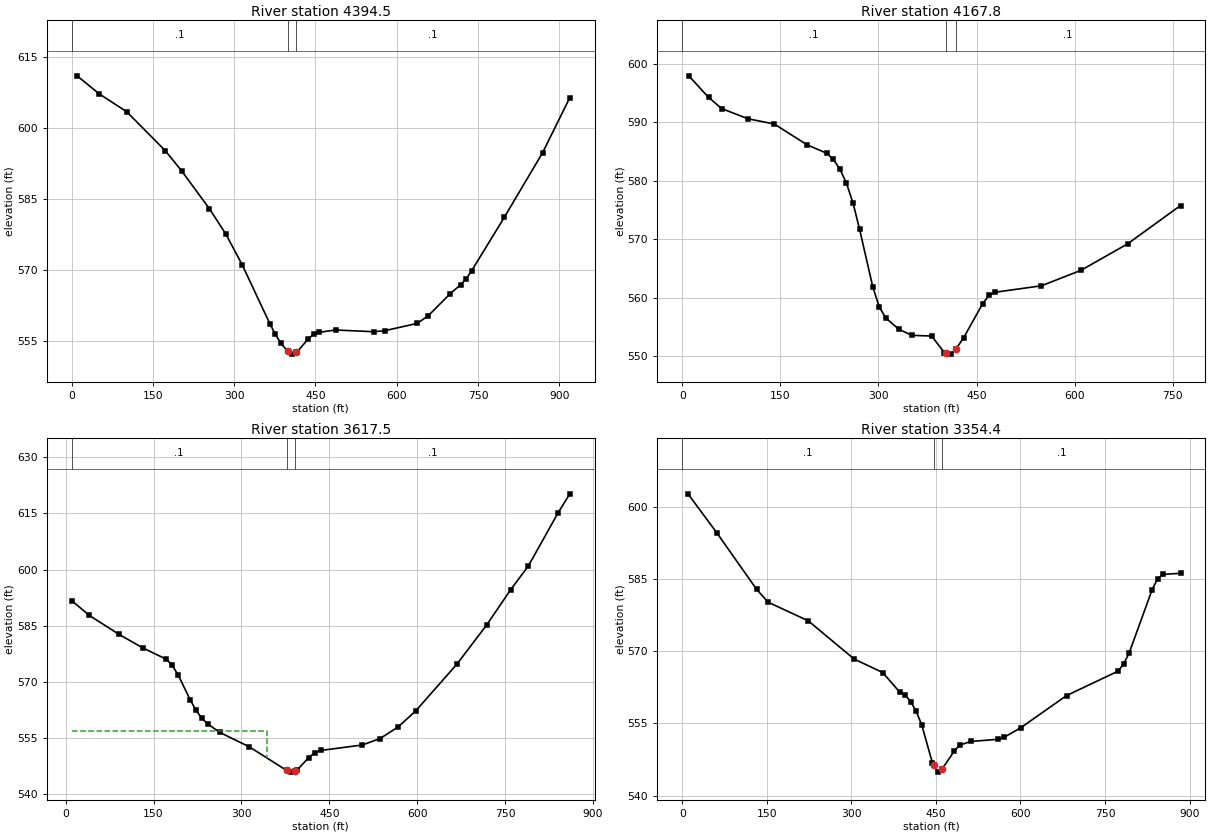
Type RM Length L Ch R = 1 ,4394.5  ,242.8,226.7,211.6
XS GIS Cut Line= 3
     1529172.172      498992.702     1529540.384      498820.429
     1529994.756      498582.444
#Sta/Elev= 30
    10.2  611.08    50.8  607.28   101.6   603.5   172.8  595.27   203.3  590.96
   254.1  583.02   284.6  577.64   315.1  571.06   365.9  558.67     376  556.43
   386.2  554.55     399  552.81   406.5  552.25     414  552.64   416.6  552.77
   436.7  555.49   446.7  556.48   456.8  556.86     487  557.35   557.4  556.99
   577.5  557.19   637.8  558.75     658  560.35   698.2  564.98   718.3  566.96
   728.4  568.22   738.4  569.91   798.8  581.24   869.2  594.85   919.4  606.49
#Mann= 3 , 0 , 0
       0      .1       0     399    .045       0     414      .1       0
Bank Sta=399,414
XS Rating Curve= 0 ,0
Exp/Cntr=0.3,0.1

Type RM Length L Ch R = 1 ,4167.8  ,543,550.3,575.5
XS GIS Cut Line= 4
     1529330.678      499058.624     1529695.111      498985.737
     1529742.572       498878.95     1530012.083      498833.184
#Sta/Elev= 30
      10  597.96    40.2  594.28    60.3  592.36   100.4  590.61   140.6  589.72
   190.8  586.16     221   584.7     231  583.65   241.1  581.99   251.1  579.59
   261.2  576.17   271.2  571.69   291.3  561.87   301.3  558.38   311.4  556.49
   331.5  554.55   351.6  553.53   381.4  553.42   400.9  550.57   403.1  550.51
   410.6  550.32   418.1  551.13   430.1  553.09   459.3  558.93     469   560.4
   478.8  560.92   549.3  562.02     610  564.68   680.9  569.19   761.9  575.76
#Mann= 3 , 0 , 0
       0      .1       0   403.1    .045       0   418.1      .1       0
Bank Sta=403.1,418.1
XS Rating Curve= 0 ,0
Exp/Cntr=0.3,0.1

Type RM Length L Ch R = 1 ,3617.5  ,232.2,263.1,290.4
XS GIS Cut Line= 3
     1529285.051      499245.801      1529679.01      499222.627
      1530142.49      499173.382
#Sta/Elev= 30
    10.1  591.72    40.5  587.72    91.1  582.67   131.5  579.07     172  576.01
   182.1  574.37   192.3  571.74   212.5  565.21   222.6  562.35   232.7  560.22
   242.9  558.69   263.1  556.48   313.7   552.6     377  546.34   384.5  545.86
     392  546.21   394.6  546.33   414.9  549.75     425     551   435.2  551.65
   506.1   553.1   536.5  554.82   566.9  557.86   597.3  562.17   668.2  574.78
   718.9  585.23   759.4  594.56   789.8  600.94   840.5  615.13   860.7  620.23
#Mann= 3 , 0 , 0
    10.1      .1       0     377    .045       0     392      .1       0
#XS Ineff= 2 , 0
          344.48  556.83
Permanent Ineff=
       F       F
Bank Sta=377,392
XS Rating Curve= 0 ,0
Exp/Cntr=0.3,0.1

Type RM Length L Ch R = 1 ,3354.4  ,3416.3,3354.4,3302.3
XS GIS Cut Line= 4
     1529206.541      499279.535     1529591.176       499312.65
      1529670.14      499445.107     1529950.338      499643.792
#Sta/Elev= 30
    10.2  602.67      61  594.63   132.1  582.81   152.4  580.16   223.5   576.3
   304.8  568.37   355.6  565.56   386.1  561.45   395.7  560.88   405.3  559.49
     415  557.49   424.6  554.77   443.9  546.75     446  546.35   453.5  544.88
     461  545.53   482.4  549.23   492.1  550.48   511.4  551.24   560.5   551.7
   570.6  552.09   600.9  554.13   681.7  560.78   772.6  565.82   782.7  567.28
   792.8  569.65   833.2  582.68   843.3  585.08   853.4  585.93   883.8  586.18
#Mann= 3 , 0 , 0
       0      .1       0     446    .045       0     461      .1       0
Bank Sta=446,461
XS Rating Curve= 0 ,0
Exp/Cntr=0.3,0.1

Chan Stop Cuts=-1
Use User Specified Reach Order=0